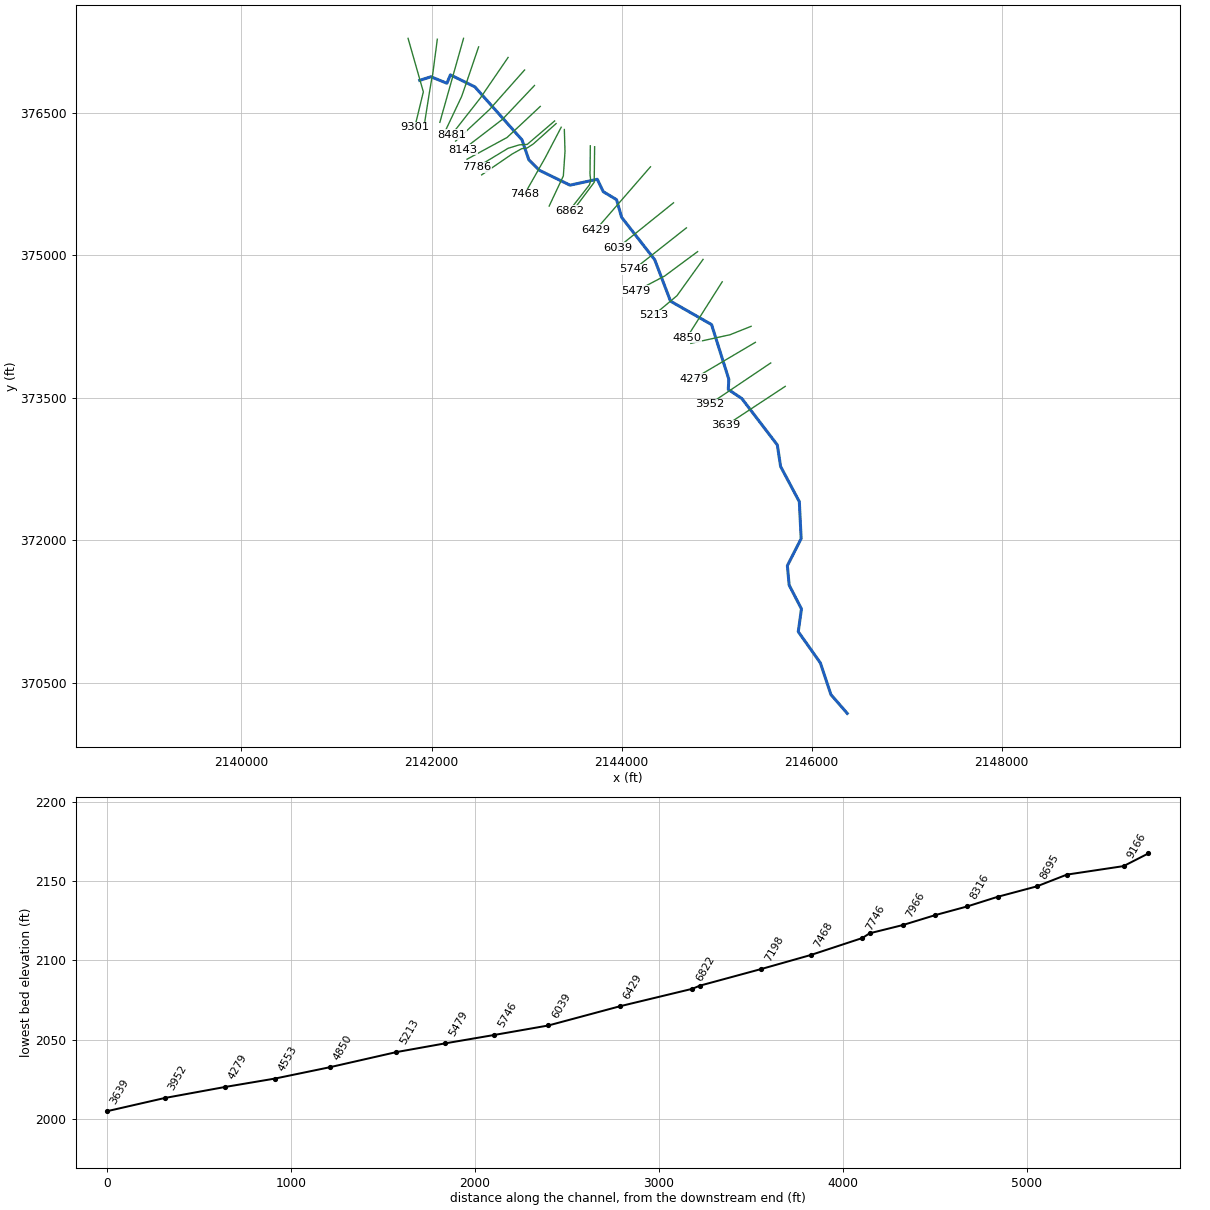
--- DRYRN.prj (project) ---

Proj Title=DRYRN
Current Plan=p01
Default Exp/Contr=0.3,0.1
English Units
Geom File=g01
Flow File=f01
Plan File=p01
Y Axis Title=Elevation
X Axis Title(PF)=Main Channel Distance
X Axis Title(XS)=Station
BEGIN DESCRIPTION:
Stream Name- Dry Run
Flood Zone: Zone A
Greenbrier County, WV
County-Wide Study
WVDHSEM-2018-3, Flood Risk Project
HEC-RAS Version: 5.0.7
General Notes:
For the Hydrology regression was used.
END DESCRIPTION:
DSS Export Rating Curves= 0
DSS Export Rating Curve Sorted= 0
DSS Export Volume Flow Curves= 0
DXF Filename=A3a.
DXF OffsetX= 0
DXF OffsetY= 0
DXF ScaleX= 1
DXF ScaleY= 10

--- DRYRN.p01 (plan) ---

Plan Title=Floodplain
Program Version=5.07
Short Identifier=Floodplain
Geom File=g01
Flow File=f01
Subcritical Flow
K Sum by GR= 0
Std Step Tol= 0.01
Critical Tol= 0.01
Num of Std Step Trials= 20
Max Error Tol= 0.3
Flow Tol Ratio= 0.001
Split Flow NTrial= 30
Split Flow Tol= 0.02
Split Flow Ratio= 0.02
Log Output Level= 0
Friction Slope Method= 1
Unsteady Friction Slope Method= 2
Unsteady Bridges Friction Slope Method= 1
Parabolic Critical Depth
Global Vel Dist= 0 , 0 , 0
Global Log Level= 0
CheckData=True
Encroach Param=-1 ,0,0, 0
Computation Interval=1MIN
Output Interval=1HOUR
Instantaneous Interval=1HOUR
Mapping Interval=1HOUR
Computation Time Step Use Courant=        0
Computation Time Step Use Time Series=    0
Computation Time Step Count To Double=0
Computation Time Step Max Doubling=0
Computation Time Step Max Halving=0
Computation Time Step Residence Courant=0
Run HTab= 0
Run UNet= 0
Run Sediment= 0
Run PostProcess= 0
Run WQNet= 0
Run RASMapper= 0
UNET Theta= 1
UNET Theta Warmup= 1
UNET ZTol= 0.02
UNET ZSATol= 0.02
UNET MxIter= 20
UNET Max Iter WO Improvement= 0
UNET MaxInSteps= 0
UNET DtIC= 0
UNET DtMin= 0
UNET MaxCRTS= 20
UNET WFStab= 2
UNET SFStab= 1
UNET WFX= 1
UNET SFX= 1
UNET 1D Methodology=Finite Difference
UNET DSS MLevel= 4
UNET Pardiso=0
UNET DZMax Abort= 100
UNET Use Existing IB Tables=-1
UNET Froude Reduction=False
UNET Froude Limit= 0.8
UNET Froude Power= 4
UNET D1 Cores= 0
UNET D2 Coriolis=0
UNET D2 Cores= 0
UNET D2 Theta= 1
UNET D2 Theta Warmup= 1
UNET D2 Z Tol= 0.01
UNET D2 Volume Tol= 0.01
UNET D2 Max Iterations= 20
UNET D2 Equation= 0
UNET D2 RampUpFraction=0.1
UNET D2 TimeSlices= 1
UNET D2 BCVolumeCheck=0
UNET D1D2 MaxIter= 0
UNET D1D2 ZTol=0.01
UNET D1D2 QTol=0.1
UNET D1D2 MinQTol=1
Write IC File= 0
Write IC File at Fixed DateTime=0
Write IC File at Sim End=0
Echo Input=False
Echo Parameters=False
Echo Output=False
Write Detailed= 0
HDF Write Warmup=0
HDF Write Time Slices=0
HDF Flush=0
HDF Face Node Velocities=0
HDF Compression= 1
HDF Chunk Size= 1
HDF Spatial Parts= 1
HDF Use Max Rows=0
HDF Fixed Rows= 1
Calibration Method= 0
Calibration Iterations= 20
Calibration Max Change=0.05
Calibration Tolerance=0.2
Calibration Maximum=1.5
Calibration Minimum=0.5
Calibration Optimization Method= 1
WQ AD Non Conservative
WQ ULTIMATE=-1
WQ Max Comp Step=1HOUR
WQ Output Interval=15MIN
WQ Output Selected Increments= 0
WQ Output face flow=0
WQ Output face velocity=0
WQ Output face area=0
WQ Output face dispersion=0
WQ Output cell volume=0
WQ Output cell surface area=0
WQ Output cell continuity=0
WQ Output cumulative cell continuity=0
WQ Output face conc=0
WQ Output face dconc_dx=0
WQ Output face courant=0
WQ Output face peclet=0
WQ Output face adv mass=0
WQ Output face disp mass=0
WQ Output cell mass=0
WQ Output cell source sink temp=0
WQ Output nsm pathways=0
WQ Output nsm derived pathways=0
WQ Output MaxMinRange=-1
WQ Daily Max Min Mean=-1
WQ Daily Range=0
WQ Daily Time=0
WQ Create Restart=0
WQ Fixed Restart=0
WQ System Summary=0
WQ Write To DSS=0
WQ Use Fixed Temperature=0
Sorting and Armoring Iterations= 10
XS Update Threshold= 0.02
Bed Roughness Predictor= 0
Hydraulics Update Threshold= 0.02
Energy Slope Method= 1
Volume Change Method= 1
Sediment Retention Method= 0
XS Weighting Method= 0
Number of US Weighted Cross Sections= 1
Number of DS Weighted Cross Sections= 1
Upstream XS Weight=0
Main XS Weight=1
Downstream XS Weight=0
Number of DS XS's Weighted with US Boundary= 1
Upstream Boundary Weight= 1
Weight of XSs Associated with US Boundary= 0
Number of US XS's Weighted with DS Boundary= 1
Downstream Boundary Weight= 0.5
Weight of XSs Associated with DS Boundary= 0.5
Percentile Method= 0
Sediment Output Level= 3
Mass or Volume Output= 0
Output Increment Type= 1
Profile and TS Output Increment= 1
XS Output Flag= 0
XS Output Increment= 10
Write Gradation File= 0
Read Gradation Hotstart= 0
Write HDF5 File= 1
Write Binary Output= 1
Write DSS Sediment File= 0
SV Curve= 0
Specific Gage Flag= 0

--- DRYRN.f01 (steady flow) ---

Flow Title=Flow
Program Version=5.07
Number of Profiles= 6
Profile Names=f1p,f10p,f4p,f2p,f02p,f1pplus
River Rch & RM=BEVERLYFK,Main            ,776
     323     167     225     272     456     478
River Rch & RM=BEVERLYFK,Main            ,220
     537     283     377     454     751     794
River Rch & RM=BOGGSRN,Main            ,1733
     558     295     392     472     780     825
River Rch & RM=DRYRN,Main            ,9301
     532     280     373     450     744     787
River Rch & RM=DRYRN,Main            ,8316
     594     314     418     503     829     878
River Rch & RM=DRYRN,Main            ,6862
     769     411     544     653    1070    1140
River Rch & RM=DRYRN,Main            ,5213
     898     483     637     763    1240    1330
River Rch & RM=DRYRN,Main            ,259
    1110     604     793     948    1540    1650
River Rch & RM=PNTHRCMPCK,Main            ,14558
     513     270     359     434     718     758
River Rch & RM=PNTHRCMPCK,Main            ,13060
     599     317     422     508     836     886
River Rch & RM=PNTHRCMPCK,Main            ,10150
     873     469     619     742    1210    1290
River Rch & RM=PNTHRCMPCK,Main            ,8160
     976     526     693     830    1350    1440
River Rch & RM=PNTHRCMPCK,Main            ,6420
    1080     588     772     923    1500    1600
River Rch & RM=RCKCMPRN,Main            ,4355
     581     307     409     492     812     860
River Rch & RM=RCKCMPRN,Main            ,1618
     692     368     488     586     963    1020
River Rch & RM=ROBBINSRN,Main            ,27789
     907     488     643     771    1260    1340
River Rch & RM=ROBBINSRN,Main            ,27014
    1170     638     837    1000    1620    1740
River Rch & RM=ROBBINSRN,Main            ,21785
    1330     728     953    1140    1830    1970
River Rch & RM=ROBBINSRN,Main            ,16781
    1830    1010    1320    1570    2500    2710
River Rch & RM=ROBBINSRN,Main            ,10962
    2050    1140    1480    1750    2790    3030
River Rch & RM=SPRINGCKT3,Main            ,6529
     583     309     410     494     815     863
River Rch & RM=SPRINGCKT3,Main            ,3093
     683     363     482     579     951    1010
River Rch & RM=SPRINGCKT3,Main            ,434
     860     462     609     730    1190    1270
Boundary for River Rch & Prof#=BEVERLYFK,Main            , 1
Up Type= 0
Dn Type= 3
Dn Slope=0.045649
Boundary for River Rch & Prof#=BEVERLYFK,Main            , 2
Up Type= 0
Dn Type= 3
Dn Slope=0.045649
Boundary for River Rch & Prof#=BEVERLYFK,Main            , 3
Up Type= 0
Dn Type= 3
Dn Slope=0.045649
Boundary for River Rch & Prof#=BEVERLYFK,Main            , 4
Up Type= 0
Dn Type= 3
Dn Slope=0.045649
Boundary for River Rch & Prof#=BEVERLYFK,Main            , 5
Up Type= 0
Dn Type= 3
Dn Slope=0.045649
Boundary for River Rch & Prof#=BEVERLYFK,Main            , 6
Up Type= 0
Dn Type= 3
Dn Slope=0.045649
Boundary for River Rch & Prof#=BOGGSRN,Main            , 1
Up Type= 0
Dn Type= 3
Dn Slope=0.043074
Boundary for River Rch & Prof#=BOGGSRN,Main            , 2
Up Type= 0
Dn Type= 3
Dn Slope=0.043074
Boundary for River Rch & Prof#=BOGGSRN,Main            , 3
Up Type= 0
Dn Type= 3
Dn Slope=0.043074
Boundary for River Rch & Prof#=BOGGSRN,Main            , 4
Up Type= 0
Dn Type= 3
Dn Slope=0.043074
Boundary for River Rch & Prof#=BOGGSRN,Main            , 5
Up Type= 0
Dn Type= 3
Dn Slope=0.043074
Boundary for River Rch & Prof#=BOGGSRN,Main            , 6
Up Type= 0
Dn Type= 3
Dn Slope=0.043074
Boundary for River Rch & Prof#=DRYRN,Main            , 1
Up Type= 0
Dn Type= 3
Dn Slope=0.021282
Boundary for River Rch & Prof#=DRYRN,Main            , 2
Up Type= 0
Dn Type= 3
Dn Slope=0.021282
Boundary for River Rch & Prof#=DRYRN,Main            , 3
Up Type= 0
Dn Type= 3
Dn Slope=0.021282
Boundary for River Rch & Prof#=DRYRN,Main            , 4
Up Type= 0
Dn Type= 3
Dn Slope=0.021282
Boundary for River Rch & Prof#=DRYRN,Main            , 5
Up Type= 0
Dn Type= 3
Dn Slope=0.021282
Boundary for River Rch & Prof#=DRYRN,Main            , 6
Up Type= 0
Dn Type= 3
Dn Slope=0.021282
Boundary for River Rch & Prof#=PNTHRCMPCK,Main            , 1
Up Type= 0
Dn Type= 3
Dn Slope=0.02712
Boundary for River Rch & Prof#=PNTHRCMPCK,Main            , 2
Up Type= 0
Dn Type= 3
Dn Slope=0.02712
Boundary for River Rch & Prof#=PNTHRCMPCK,Main            , 3
Up Type= 0
Dn Type= 3
Dn Slope=0.02712
Boundary for River Rch & Prof#=PNTHRCMPCK,Main            , 4
Up Type= 0
Dn Type= 3
Dn Slope=0.02712
Boundary for River Rch & Prof#=PNTHRCMPCK,Main            , 5
Up Type= 0
Dn Type= 3
Dn Slope=0.02712
Boundary for River Rch & Prof#=PNTHRCMPCK,Main            , 6
Up Type= 0
Dn Type= 3
Dn Slope=0.02712
Boundary for River Rch & Prof#=RCKCMPRN,Main            , 1
Up Type= 0
Dn Type= 3
Dn Slope=0.013802
Boundary for River Rch & Prof#=RCKCMPRN,Main            , 2
Up Type= 0
Dn Type= 3
Dn Slope=0.013802
Boundary for River Rch & Prof#=RCKCMPRN,Main            , 3
Up Type= 0
Dn Type= 3
Dn Slope=0.013802
Boundary for River Rch & Prof#=RCKCMPRN,Main            , 4
Up Type= 0
Dn Type= 3
Dn Slope=0.013802
Boundary for River Rch & Prof#=RCKCMPRN,Main            , 5
Up Type= 0
Dn Type= 3
Dn Slope=0.013802
Boundary for River Rch & Prof#=RCKCMPRN,Main            , 6
Up Type= 0
Dn Type= 3
Dn Slope=0.013802
Boundary for River Rch & Prof#=ROBBINSRN,Main            , 1
Up Type= 0
Dn Type= 3
Dn Slope=0.010317
Boundary for River Rch & Prof#=ROBBINSRN,Main            , 2
Up Type= 0
Dn Type= 3
Dn Slope=0.010317
Boundary for River Rch & Prof#=ROBBINSRN,Main            , 3
Up Type= 0
Dn Type= 3
Dn Slope=0.010317
Boundary for River Rch & Prof#=ROBBINSRN,Main            , 4
Up Type= 0
Dn Type= 3
Dn Slope=0.010317
Boundary for River Rch & Prof#=ROBBINSRN,Main            , 5
Up Type= 0
Dn Type= 3
Dn Slope=0.010317
Boundary for River Rch & Prof#=ROBBINSRN,Main            , 6
Up Type= 0
Dn Type= 3
Dn Slope=0.010317
Boundary for River Rch & Prof#=SPRINGCKT3,Main            , 1
Up Type= 0
Dn Type= 3
Dn Slope=0.016207
Boundary for River Rch & Prof#=SPRINGCKT3,Main            , 2
Up Type= 0
Dn Type= 3
Dn Slope=0.016207
Boundary for River Rch & Prof#=SPRINGCKT3,Main            , 3
Up Type= 0
Dn Type= 3
Dn Slope=0.016207
Boundary for River Rch & Prof#=SPRINGCKT3,Main            , 4
Up Type= 0
Dn Type= 3
Dn Slope=0.016207
Boundary for River Rch & Prof#=SPRINGCKT3,Main            , 5
Up Type= 0
Dn Type= 3
Dn Slope=0.016207
Boundary for River Rch & Prof#=SPRINGCKT3,Main            , 6
Up Type= 0
Dn Type= 3
Dn Slope=0.016207
DSS Import GetInterval= 0
DSS Import GetPeak= 0
DSS Import FillOption= 0

--- DRYRN.g01 (geometry) ---

Geom Title=Geometry
Program Version=5.07

River Reach=DRYRN           ,Main
Reach XY= 30
2141876.05999088376839.8398868142141993.83993906376877.539942637
2142162.31007455376809.3100922262142198.85987023376897.450007811
 2142456.5899978376771.2101028112142952.19989897376213.749931648
2143024.28997789376004.1601277292143134.48988873375893.729902387
2143457.79009514375736.660006568 2143744.6799413375798.759947971
2143807.68014339375668.2198547272143947.40000831375584.289904475
 2144000.8999013 375398.370000722144349.37000489374951.880080059
2144515.36015847374515.8701253092144947.56992397374269.249883637
2145128.93012555373694.2300363032145123.52003139373586.760106891
2145265.92985155373491.1198782322145639.56000981373002.679910228
2145673.99990155372776.2899430542145871.09005855372405.669949397
2145890.29015139 372017.190083312145745.11983806 371731.79006356
 2145763.9298398371527.9299069792145893.54014489 371276.95993647
2145859.86993663371037.6700607242146092.10011522370709.429903567
2146203.15993246 370376.029979812146375.36368696370177.721338707

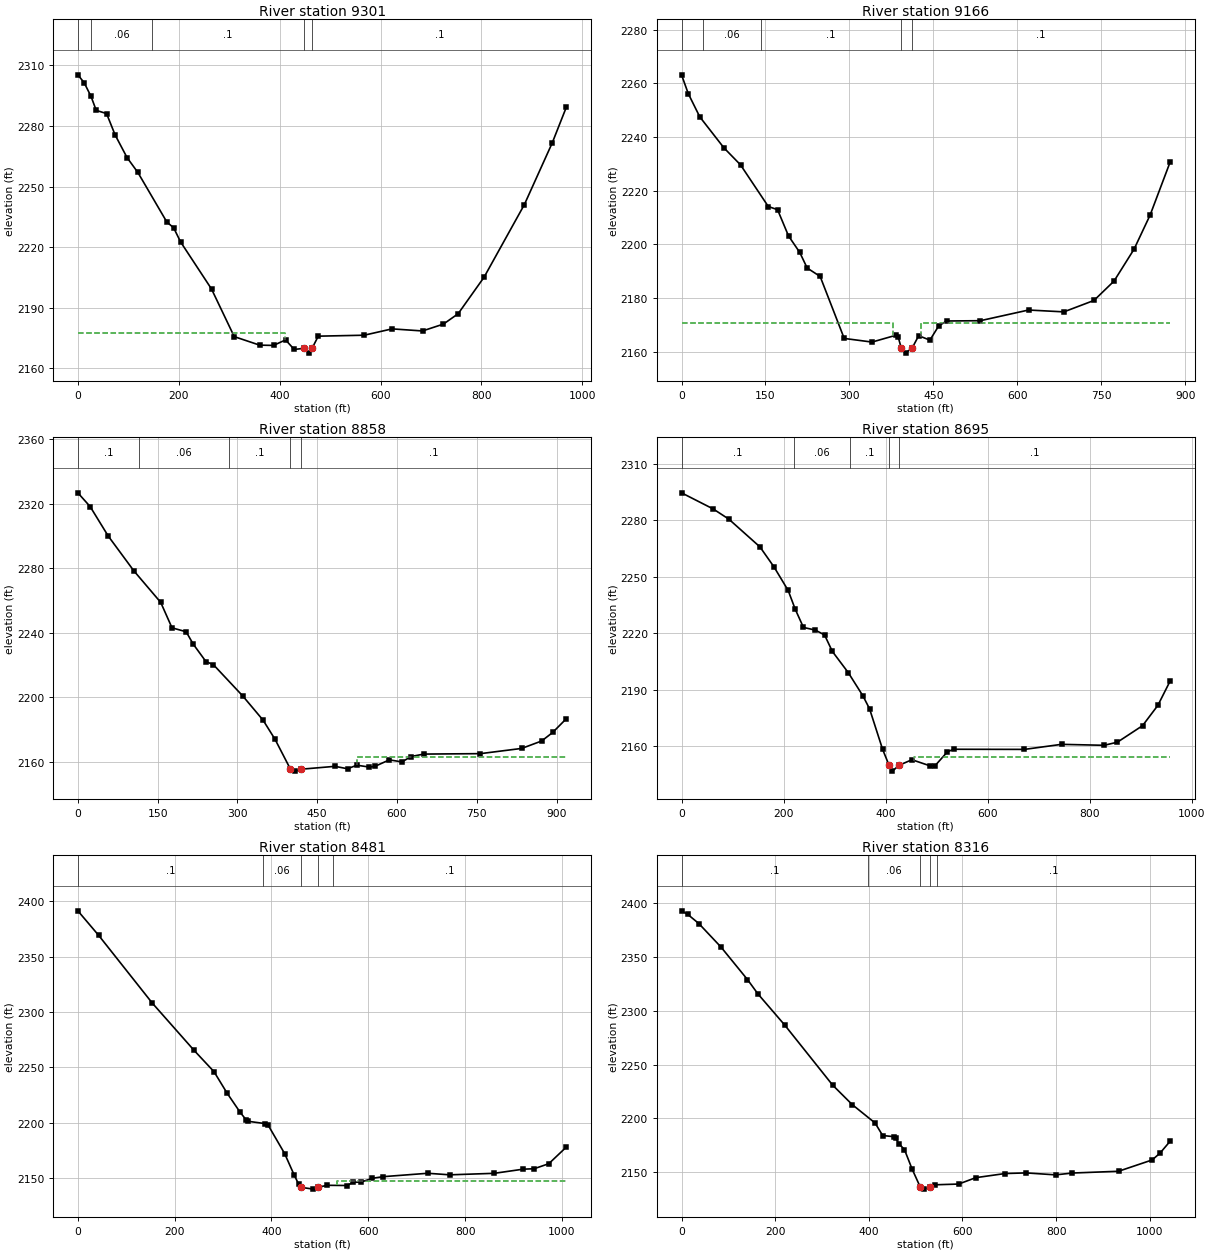
Type RM Length L Ch R = 1 ,9301    ,138.7,135.2,128.8
XS GIS Cut Line= 3
2141753.50872681377281.6926776472141914.09895681376718.541572973
2141823.91705056376346.624337807
#Sta/Elev= 30
       0  2305.3    12.5 2301.41    26.2 2294.58    36.4  2287.7    56.9 2286.12
    73.9 2275.53    97.6 2264.29   118.9 2256.98   176.3 2232.45   189.9 2229.54
   203.6 2222.57   264.9 2199.26     310 2175.66   360.4 2171.44   387.8 2171.31
   411.7 2174.04   428.8 2169.33  447.772169.827   458.7 2167.49  464.552170.024
   476.5 2175.89   567.5 2176.36   622.8  2179.5   683.1 2178.47   724.6 2181.87
   753.7 2186.99   805.1 2205.08     885 2241.05   940.2 2271.58   968.3 2289.36
#Mann= 5 ,-1 , 0
       0      .1       0    26.2     .06       0  147.56      .1       0
  447.77    .045       0  464.55      .1       0
#XS Ineff= 2 , 0
           410.3 2177.29
Permanent Ineff=
       F       F
Bank Sta=447.77,464.55
XS Rating Curve= 0 ,0
Exp/Cntr=0.3,0.1

Type RM Length L Ch R = 1 ,9166    ,307.1,308.1,303.2
XS GIS Cut Line= 5
2142061.16460755377272.4535228912142011.68570389376895.717399731
2142001.26905805376849.7106019712141976.09522389376700.404798225
2141930.08842614376409.606167227
#Sta/Elev= 30
       0 2263.23    12.1  2256.2    32.6 2247.57    75.6 2236.05   105.4 2229.67
   155.1 2214.13   171.6 2212.96   191.2 2203.17   211.3 2197.01   224.5 2191.21
   247.7 2188.07   290.7 2164.96   340.4  2163.6   383.4 2166.16   387.2 2165.48
   392.6 2161.36   400.3 2159.48   412.3 2161.47   423.8 2165.97   443.8 2164.33
   459.7 2169.66   473.9 2171.46     534 2171.57   620.1 2175.55   683.2 2174.86
     737 2179.12   772.9 2186.35   808.7 2198.26   837.4 2210.99     873 2230.66
#Mann= 5 ,-1 , 0
       0      .1       0   38.75     .06       0  142.13      .1       0
   392.6    .045       0   412.3      .1       0
#XS Ineff= 2 ,-1
       0  378.04 2170.78  427.84  872.97 2170.78
Permanent Ineff=
       F       F
Bank Sta=392.6,412.3
XS Rating Curve= 0 ,0
Exp/Cntr=0.3,0.1

Type RM Length L Ch R = 1 ,8858    ,164.4,163.1,163
XS GIS Cut Line= 2
2142337.20637831 377282.002060222142087.87879297376398.059274316
#Sta/Elev= 30
       0 2326.67    23.1 2318.15    57.2 2299.83   105.2 2278.34   155.8 2258.73
     177 2242.97   203.6 2240.53   216.9 2232.86   240.8 2222.05   254.9 2220.09
     310 2200.72   348.2 2185.72   370.8 2173.78  399.29 2155.58   408.3 2154.12
   419.62155.305   483.3 2157.09   507.1 2155.58   524.2 2157.79     548 2156.65
   558.3 2157.04   585.5 2161.11   609.4 2159.83   626.4 2163.18   650.3 2164.69
   756.7 2164.96   834.4  2168.2   871.9 2172.81   892.5 2178.07   918.4 2186.67
#Mann= 5 ,-1 , 0
       0      .1       0  115.45     .06       0   283.5      .1       0
  399.29    .045       0   419.6      .1       0
#XS Ineff= 2 , 0
                          524.23         2162.75
Permanent Ineff=
       F       F
Bank Sta=399.29,419.6
XS Rating Curve= 0 ,0
Exp/Cntr=0.3,0.1

Type RM Length L Ch R = 1 ,8695    ,215.3,213.6,209.8
XS GIS Cut Line= 4
2142495.62666513377191.9415448162142374.09869297376834.302496314
2142316.80714089376669.3720518952142143.19593956 376303.05257456
#Sta/Elev= 30
       0 2294.48    62.2  2285.9    92.8  2280.5   153.7 2265.78   181.3 2255.13
     209 2242.67   222.9 2232.68     239 2223.02   262.3  2221.6   280.4 2219.01
   295.6  2210.3   326.8 2199.04   355.4 2186.77   368.6 2179.81   394.1 2158.34
  406.822149.836   413.5 2146.72  426.222149.815   451.7 2152.77   486.5 2149.59
   496.9 2149.59   521.2 2156.95   533.3 2158.33   672.3 2158.26   744.9 2160.94
   828.4 2160.43   854.4 2162.08   903.7 2170.85   933.7 2181.61   957.7  2194.5
#Mann= 5 ,-1 , 0
       0      .1       0  221.12     .06       0   329.8      .1       0
  406.82    .045       0  426.22      .1       0
#XS Ineff= 2 , 0
                          456.35         2154.34
Permanent Ineff=
       F       F
Bank Sta=406.82,426.22
XS Rating Curve= 0 ,0
Exp/Cntr=0.3,0.1

Type RM Length L Ch R = 1 ,8481    ,165.6,165.5,157.5
XS GIS Cut Line= 3
2142806.02860339377080.8302184792142512.62597497 376652.01086615
2142210.54258963376266.594314143
#Sta/Elev= 30
       0 2391.39    42.9 2369.29   153.8 2308.08   240.3 2265.31   281.3 2246.16
   307.9 2227.07   335.5 2209.35   347.3 2202.88   352.1 2201.34   387.5 2199.24
   393.4 2197.65   427.2 2172.23     447 2152.77   455.9 2144.83  460.772141.765
   486.3 2140.11  496.712141.891   515.4 2143.57   556.1 2143.37   568.7 2146.26
   585.1 2146.46   608.4  2149.9   631.1 2151.37   722.8 2154.42   768.6 2153.02
   860.4 2154.39   919.9 2158.12   942.6 2158.52   972.9 2163.06  1009.3 2178.14
#Mann= 5 ,-1 , 0
       0      .1       0  382.34     .06       0  460.77    .045       0
  496.71     .06       0  526.13      .1       0
#XS Ineff= 1 ,-1
  535.08 1009.28 2147.03
Permanent Ineff=
       F
Bank Sta=460.77,496.71
XS Rating Curve= 0 ,0
Exp/Cntr=0.3,0.1

Type RM Length L Ch R = 1 ,8316    ,173.5,173.3,172.8
XS GIS Cut Line= 3
2142979.63980472376948.8859285562142609.84822147376532.219110981
2142253.94538997 376200.62200515
#Sta/Elev= 30
       0 2392.99      13 2389.78    36.9 2381.19    84.4 2359.23   140.9 2329.01
   163.3 2315.62   220.5 2286.66   322.7 2230.85   364.5 2212.74   413.4 2195.58
   429.6 2183.93   452.9 2182.88   457.5 2181.24   464.5 2176.18   476.1 2170.91
   492.3 2152.91  509.632136.222   517.9 2134.04  530.882136.484   541.2 2138.07
   591.9 2138.76   628.4  2144.7   691.2 2148.56   736.3 2149.13   798.9 2147.31
   834.7 2149.01   933.4 2150.66  1005.1 2161.18  1021.7 2167.38  1043.5 2178.56
#Mann= 5 ,-1 , 0
       0      .1       0  398.05     .06       0  509.63    .045       0
  530.88     .06       0  546.14      .1       0
Bank Sta=509.63,530.88
XS Rating Curve= 0 ,0
Exp/Cntr=0.3,0.1

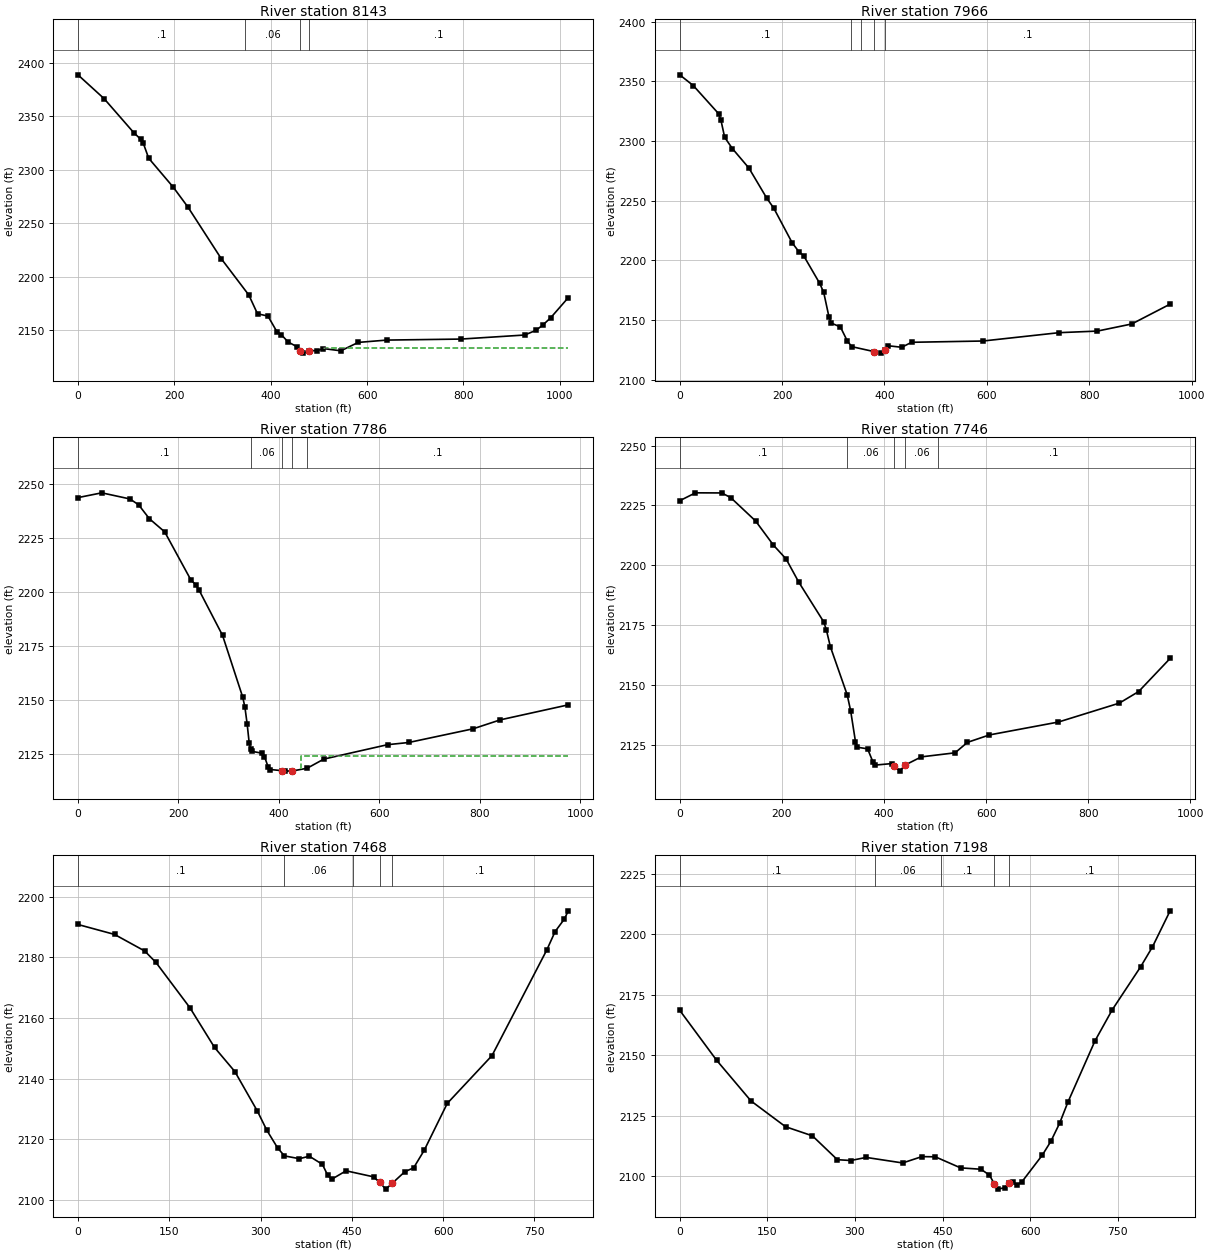
Type RM Length L Ch R = 1 ,8143    ,177,176.7,176
XS GIS Cut Line= 3
2143083.80659114376785.691373065 2142747.0008343376429.788541555
 2142328.5981278376108.608081564
#Sta/Elev= 30
       0 2388.65    54.3 2366.39   115.7 2334.69   130.7 2328.24   135.4 2324.97
   146.8 2310.71   197.5 2283.82   228.1 2265.17   297.7 2216.63   354.6 2182.86
   372.6 2165.33   394.2 2163.26   413.3 2148.25   422.3 2145.68   436.1    2139
   453.9  2134.7   460.62130.794   467.5 2128.59  479.572130.929   496.4 2130.91
   509.5 2132.82   545.5 2130.77   581.7 2138.62   640.9 2140.78   794.9 2141.73
   926.9 2145.51   950.3 2149.87   964.5 2154.79     981 2161.68  1017.5 2180.49
#Mann= 4 ,-1 , 0
       0      .1       0  347.56     .06       0   460.6    .045       0
  479.57      .1       0
#XS Ineff= 1 ,-1
  509.71 1017.47 2132.93
Permanent Ineff=
       F
Bank Sta=460.6,479.57
XS Rating Curve= 0 ,0
Exp/Cntr=0.3,0.1

Type RM Length L Ch R = 1 ,7966    ,186.7,180.1,172.8
XS GIS Cut Line= 3
2143144.57057722376565.2052654772142795.61195755376238.816482559
2142373.73714514376009.649618059
#Sta/Elev= 30
       0 2355.49    26.5 2346.49    75.9 2322.95    80.4 2317.69    87.8 2303.13
   102.8 2293.72   135.1 2277.41   170.2 2252.02   183.7 2243.81   219.6  2214.8
   232.5 2207.44   242.1 2203.92   273.6 2180.65   281.3 2173.11   291.5 2152.74
     296 2147.45   313.8 2144.29   327.7  2132.2   336.4  2127.7  379.952123.557
   392.7 2122.31  400.12 2125.04   406.6 2128.52   433.7 2127.21   452.9 2131.39
   592.3 2132.46   741.1 2139.45   815.8 2140.78     883 2146.74   957.9 2163.36
#Mann= 5 ,-1 , 0
       0      .1       0  335.39     .06       0   354.8      .1       0
  379.95    .045       0  400.12      .1       0
Bank Sta=379.95,400.12
XS Rating Curve= 0 ,0
Exp/Cntr=0.5,0.3

Type RM Length L Ch R = 1 ,7786    ,38.9,39.6,40.3
XS GIS Cut Line= 5
2143295.73547241 376412.452890682143007.13973667376165.581839622
2142923.69036729376160.9457635462142806.49617077376124.861526047
2142472.83196888 375923.34686464
#Sta/Elev= 30
       0  2243.9    47.4 2246.12   103.5 2243.28   120.8 2240.56   142.3 2234.08
   172.6 2228.04     225 2205.63   234.3  2203.6   240.9 2201.09   287.8 2180.02
     328 2151.34   332.3  2146.7   336.7 2139.01   340.9 2129.95   343.7 2127.34
   346.9 2126.26     367  2125.4   371.2 2123.86   378.6 2119.01   383.1 2117.87
   406.82117.313   412.4 2117.12   426.8  2117.2     456 2118.45   489.3  2122.7
   616.1 2129.38   658.2 2130.39   786.5 2136.75   840.3 2140.88   975.8 2147.84
#Mann= 5 ,-1 , 0
       0      .1       0   343.7     .06       0   406.8    .045       0
   426.8     .06       0     456      .1       0
#XS Ineff= 2 , 0
                          443.62         2124.22
Permanent Ineff=
       F       F
Bank Sta=406.8,426.8
XS Rating Curve= 0 ,0
Exp/Cntr(USF)=0,0
Exp/Cntr=0.5,0.3

Type RM Length L Ch R = 1 ,7746    ,268.5,278.5,287.1
XS GIS Cut Line= 6
2143311.23723863376384.649852306 2143069.9175113376169.372067645
2143007.13973667376128.4932310122142949.15061537376120.920395025
2142847.19511204376063.5881659452142528.16874284375845.320471155
#Sta/Elev= 30
       0 2226.97    30.8 2230.27    82.2 2230.22    99.8 2228.29   148.6 2218.52
   183.6 2208.42   208.3 2202.68   232.9 2193.08   282.2 2176.35   287.1 2173.12
     295 2166.07   327.9 2146.03   334.7 2139.35   344.2 2126.41   347.4 2124.14
   367.9 2123.45   378.7 2117.82   382.7 2116.67   414.9 2117.29  419.952116.296
   431.4 2114.15  440.232116.566   473.1  2120.1   539.2 2121.79   563.4 2126.15
   606.6 2129.26   741.7 2134.64   860.8 2142.52   898.7 2147.35   960.3 2161.17
#Mann= 5 ,-1 , 0
       0      .1       0  326.87     .06       0  419.95    .045       0
  440.23     .06       0  505.98      .1       0
Bank Sta=419.95,440.23
XS Rating Curve= 0 ,0
Exp/Cntr=0.5,0.3

Type RM Length L Ch R = 1 ,7468    ,268.9,270,270.4
XS GIS Cut Line= 3
2143365.05668481376346.4553748972143193.18137239376018.330374971
2142977.90391581375639.858034804
#Sta/Elev= 30
       0 2190.87    60.1 2187.59   109.7 2182.12   128.2 2178.34     184 2163.39
   224.5 2150.26   257.8 2142.33   294.9 2129.25   310.4 2122.93   328.2 2117.08
   339.3 2114.47   363.9 2113.55   380.2 2114.37   401.7 2111.68   410.4 2108.08
   416.9 2106.75   440.6 2109.55   485.9 2107.55  495.68  2105.7   505.9  2103.5
  516.142105.378   537.2 2109.26   551.6 2110.52     569 2116.32   606.9 2131.81
   680.4 2147.59   770.6 2182.53   784.1 2188.54   799.2 2192.64   805.8 2195.38
#Mann= 5 ,-1 , 0
       0      .1       0     339     .06       0  452.29      .1       0
  495.68    .045       0  516.14      .1       0
#XS Ineff= 2 , 0
          440.99 2108.01
Permanent Ineff=
       F       F
Bank Sta=495.68,516.14
XS Rating Curve= 0 ,0
Exp/Cntr=0.3,0.1

Type RM Length L Ch R = 1 ,7198    ,330.6,335.4,344.1
XS GIS Cut Line= 4
2143398.04251122376322.1496492332143404.98705114376089.510678813
2143387.62586538375834.3025278152143238.32038972375516.594173729
#Sta/Elev= 30
       0 2168.57      63 2147.97   122.1 2131.08   181.2 2120.44   227.2 2116.67
   269.9 2106.81   292.9 2106.47   319.2 2107.75   381.7 2105.46   414.6 2108.08
   437.6    2108   480.8 2103.43   515.8 2102.86   530.3 2100.43  538.842096.749
   544.8 2094.64   556.3 2095.23     5642097.095   570.1 2097.52   577.4 2096.35
   585.9 2097.67   620.9 2108.73   635.4 2114.39   650.4 2121.87   664.8  2130.7
     711 2155.94   740.5 2168.77   789.2 2186.58   809.4  2194.8   839.6  2209.7
#Mann= 5 ,-1 , 0
       0      .1       0  333.83     .06       0  447.06      .1       0
  538.84    .045       0     564      .1       0
Bank Sta=538.84,564
XS Rating Curve= 0 ,0
Exp/Cntr=0.5,0.3

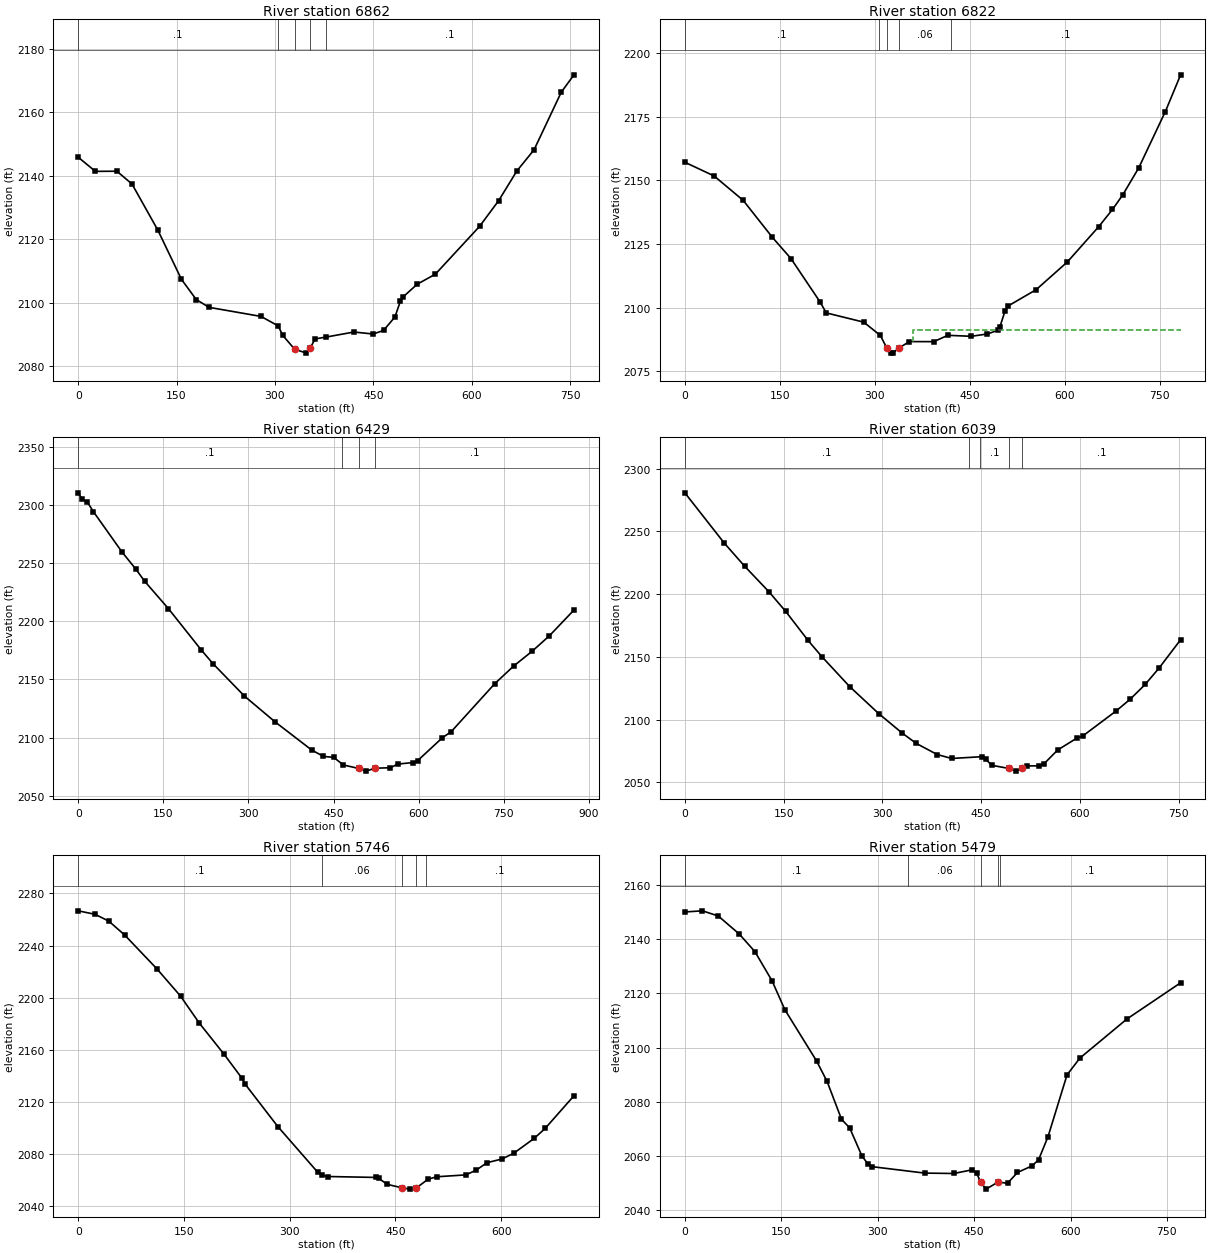
Type RM Length L Ch R = 1 ,6862    ,41.8,40.6,39.5
XS GIS Cut Line= 5
2143671.37418909 376150.823567272143668.24483774375852.492071765
2143675.54665756375783.6463420342143661.98613504375739.835423113
2143451.27647737375469.668089772
#Sta/Elev= 30
       0 2145.89    26.2 2141.43      59 2141.47      82 2137.45   121.4 2122.91
   157.4 2107.38     180    2101   199.5 2098.53   278.8 2095.67   305.1 2092.67
   311.7 2089.75     330 2085.34     348 2084.09   353.7 2085.62   361.2 2088.57
   377.6 2089.14   420.6 2090.75   449.7 2090.12   465.6 2091.24     483 2095.48
   491.3 2100.44     496 2101.92     517 2105.83   544.7    2109     612 2124.05
   641.1 2132.15     669 2141.56   695.2 2148.23   736.8 2166.44   756.1 2171.88
#Mann= 5 ,-1 , 0
       0      .1       0   305.1     .06       0     330    .045       0
   353.7     .06       0   377.6      .1       0
Bank Sta=330,353.7
XS Rating Curve= 0 ,0
Exp/Cntr(USF)=0,0
Exp/Cntr=0.5,0.3

Type RM Length L Ch R = 1 ,6822    ,399.2,392.9,386.3
XS GIS Cut Line= 3
2143716.82509838376141.2584160862143712.27875939375766.594001815
2143467.48725422375440.205218896
#Sta/Elev= 30
       0  2157.1    46.2 2151.71    92.1 2142.13     138 2127.66   167.6 2119.24
   213.5 2102.21   223.3 2097.92   282.4 2094.29   308.7 2089.06   318.5 2084.28
   325.1 2082.14   328.3 2082.12     338 2084.14   354.6 2086.65     393 2086.63
   415.2 2089.12   452.1 2088.73   477.3 2089.63   493.7 2091.03   497.2 2092.26
   505.4 2098.66   509.5 2100.52   554.7 2107.06   603.9 2117.94   653.2 2131.75
   675.1 2138.54   691.5 2144.35   716.4 2154.81   758.6 2177.02   782.7 2191.44
#Mann= 5 ,-1 , 0
       0      .1       0  306.75     .06       0   318.5    .045       0
     338     .06       0  420.75      .1       0
#XS Ineff= 2 , 0
                          360.38         2091.01
Permanent Ineff=
       F       F
Bank Sta=318.5,338
XS Rating Curve= 0 ,0
Exp/Cntr=0.5,0.3

Type RM Length L Ch R = 1 ,6429    ,390.9,389.7,384.5
XS GIS Cut Line= 2
2144304.29266723375929.7885573062143731.37583405375270.066451564
#Sta/Elev= 30
       0 2310.28       7 2304.57    16.3 2302.16    26.9 2294.02    76.9 2259.62
     102 2244.45     117 2234.36   159.1  2210.7     217 2175.17   237.3 2163.61
     293 2135.61   347.1 2113.41   411.6 2089.25   432.2 2083.79   450.2 2082.98
   467.4 2076.42  494.152073.462     507 2071.14  523.612073.649   550.2 2074.06
   563.2 2077.19   590.7 2078.54     598 2080.02   641.9 2099.86   657.4 2105.04
   734.3 2146.35   767.4  2161.4     800 2174.13   830.2 2187.31   873.8  2209.6
#Mann= 4 ,-1 , 0
       0      .1       0   464.8     .06       0  494.15    .045       0
  523.61      .1       0
Bank Sta=494.15,523.61
XS Rating Curve= 0 ,0
Exp/Cntr=0.3,0.1

Type RM Length L Ch R = 1 ,6039    ,293.1,293.3,292.8
XS GIS Cut Line= 2
2144547.34828347375551.3165452332143960.54269855375079.094064474
#Sta/Elev= 30
       0 2280.81      60 2240.68    90.7  2222.4   127.7 2201.98   153.1 2186.39
   187.2 2163.15   208.3 2150.17   250.4 2126.38   294.4 2104.91   330.4 2089.23
   351.5 2081.11   383.4 2072.23   405.4 2069.09   451.4 2070.51   456.8 2068.81
     466 2063.68  491.882061.168   503.1    2059  512.172061.131   519.7 2063.14
   538.4 2063.23   545.2  2064.6   566.5 2075.88   595.7 2085.36   604.2 2086.88
   655.5 2107.06   676.4 2116.25   699.4 2128.12   720.4 2141.11   753.2 2163.74
#Mann= 5 ,-1 , 0
       0      .1       0  431.63     .06       0   449.1      .1       0
  491.88    .045       0  512.17      .1       0
Bank Sta=491.88,512.17
XS Rating Curve= 0 ,0
Exp/Cntr=0.3,0.1

Type RM Length L Ch R = 1 ,5746    ,267.6,266.6,263.7
XS GIS Cut Line= 2
2144682.76500739375287.4276373092144130.68146589374851.663745061
#Sta/Elev= 30
       0 2266.62      24 2263.94    43.4  2258.7    65.8 2248.11   111.8    2222
   145.2 2201.15   171.8 2180.44   206.9 2156.56   232.1 2138.29   237.1  2133.4
   283.1  2101.1     340 2065.86   345.8 2063.76   353.9 2062.73   421.8 2062.02
   426.4  2061.2   438.6 2056.68  459.53    2054   470.8 2053.04  479.552053.914
   496.5 2060.71   508.8 2062.54   549.8 2063.96   564.3 2067.52   579.9 2073.32
   600.8 2076.13   617.5 2080.44   646.8 2091.96   662.4 2099.63   703.3 2124.71
#Mann= 5 ,-1 , 0
       0      .1       0  345.79     .06       0  459.53    .045       0
  479.55     .06       0  492.92      .1       0
Bank Sta=459.53,479.55
XS Rating Curve= 0 ,0
Exp/Cntr=0.3,0.1

Type RM Length L Ch R = 1 ,5479    ,260.6,266.5,267.1
XS GIS Cut Line= 3
2144800.82054555375037.4274811452144453.59814289 374780.48311314
2144153.25097455374622.496880561
#Sta/Elev= 30
       0 2150.06    27.4 2150.48    51.9 2148.58    84.6 2141.93   109.1 2135.39
   135.8 2124.58   155.6 2113.97   204.9 2095.07   221.3  2087.5   243.7 2073.56
   256.5 2070.32   275.2 2060.15   284.7 2057.02   291.7 2056.03     373 2053.67
   418.3 2053.52     447 2054.88   453.8 2053.65  460.492050.245   468.6 2047.75
  487.432050.368     502  2049.9   517.4 2053.89   539.8  2056.3   550.2 2058.52
     565 2067.11   594.6 2089.94   614.6 2096.12   687.8 2110.56   771.3 2123.92
#Mann= 5 ,-1 , 0
       0      .1       0  347.22     .06       0  460.49    .045       0
  487.43     .06       0  489.67      .1       0
Bank Sta=460.49,487.43
XS Rating Curve= 0 ,0
Exp/Cntr=0.3,0.1

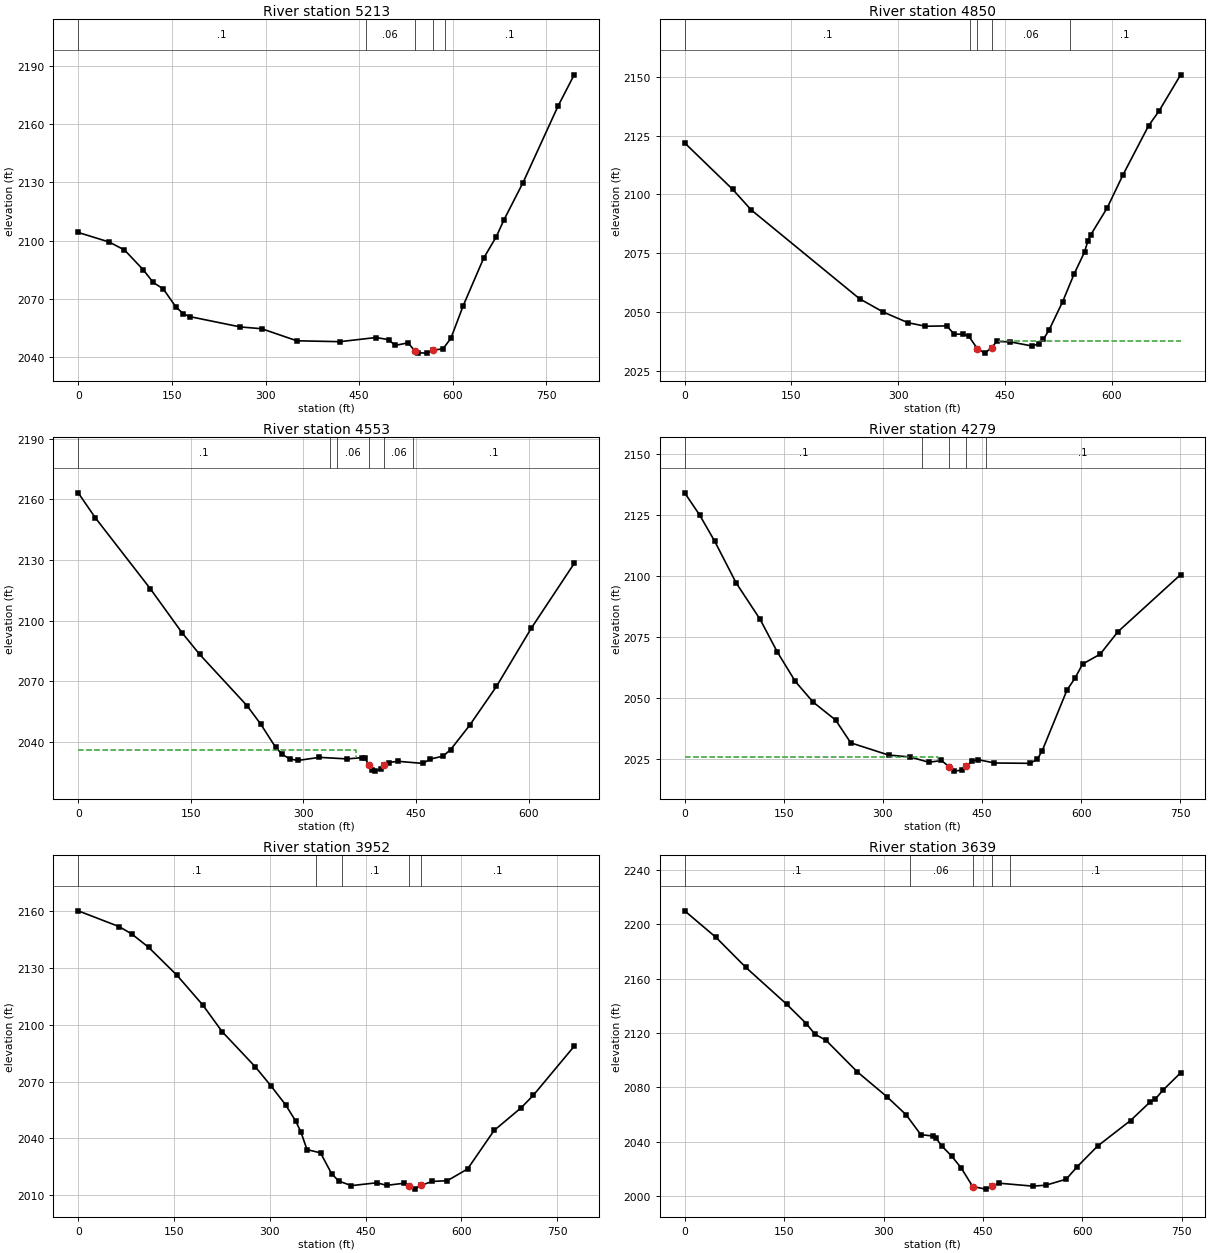
Type RM Length L Ch R = 1 ,5213    ,353.8,362.7,364.8
XS GIS Cut Line= 3
2144858.11209764374955.8302033992144583.80654389374573.885757312
2144335.54260471374365.552512556
#Sta/Elev= 30
       0 2104.28    49.2 2099.41    74.1 2095.28     104 2085.14   120.2 2078.55
   136.3 2075.22   156.5 2065.94   168.6 2062.39   178.5 2061.01   259.7 2055.68
   293.9 2054.77   350.1 2048.57   419.1 2048.11     477 2050.25   497.5 2049.13
   507.3 2046.18   528.4 2047.52  538.992043.361   544.5 2042.39   558.7 2042.22
  568.452043.819   584.1 2044.37   596.9 2049.85   616.7 2066.68   649.3 2091.03
   669.7 2102.17   681.9 2110.78   712.2 2129.78   768.2 2169.08   794.3 2185.36
#Mann= 5 ,-1 , 0
       0      .1       0  460.33     .06       0  538.99    .045       0
  568.45     .06       0  587.43      .1       0
Bank Sta=538.99,568.45
XS Rating Curve= 0 ,0
Exp/Cntr=0.3,0.1

Type RM Length L Ch R = 1 ,4850    ,304,296.9,288.2
XS GIS Cut Line= 2
2145059.50113055374719.719127059 2144686.2371133374131.177653223
#Sta/Elev= 30
       0 2121.87    67.4 2102.16    93.5 2093.43   245.7 2055.74     279  2050.1
   313.9 2045.55   338.4 2044.07   368.2 2044.21   378.8 2040.69   391.6 2040.71
   399.3 2039.81  411.152034.597   421.6 2032.66  431.152034.872   438.4  2037.6
   457.6 2037.43   488.2 2035.68   497.7 2036.65   504.2 2038.61     512 2042.44
     531  2054.4     547 2066.08   561.9 2075.58   566.6 2080.32   570.3 2082.72
   593.6 2094.22     616 2108.36   651.8 2129.11   666.5 2135.37   696.9 2150.76
#Mann= 5 ,-1 , 0
       0      .1       0  400.98     .06       0  411.15    .045       0
  431.15     .06       0  540.85      .1       0
#XS Ineff= 2 , 0
                          441.61         2037.68
Permanent Ineff=
       F       F
Bank Sta=411.15,431.15
XS Rating Curve= 0 ,0
Exp/Cntr=0.3,0.1

Type RM Length L Ch R = 1 ,4553    ,270.5,273.7,278.5
XS GIS Cut Line= 3
 2145363.3204048374250.9690803142145141.09808022374162.427590728
2144729.63991363374072.149556056
#Sta/Elev= 30
       0  2163.2    22.9  2150.8      96 2115.77   138.3 2093.99   161.8 2083.26
     225 2057.84     243 2048.83   262.9 2037.31   271.6 2033.87   281.5 2031.62
   292.5 2030.81   321.3 2032.35   358.2 2031.58   378.4 2032.24   381.8 2031.93
  387.692028.368   391.8 2026.05   395.2 2025.54   402.7 2026.53  407.792028.355
   413.7 2029.79   425.4 2030.41     459 2029.36   468.8 2031.48   485.9 2032.96
     496 2036.18   521.2 2048.15     557 2067.42   603.4 2096.23   660.5 2128.25
#Mann= 6 ,-1 , 0
       0      .1       0  335.52    .055       0  344.83     .06       0
  387.69    .045       0  407.79     .06       0  445.73      .1       0
#XS Ineff= 2 , 0
          369.98 2035.97
Permanent Ineff=
       F       F
Bank Sta=387.69,407.79
XS Rating Curve= 0 ,0
Exp/Cntr=0.3,0.1

Type RM Length L Ch R = 1 ,4279    ,325.4,327,324
XS GIS Cut Line= 2
2145408.45942214374082.5665299742144762.62606813373700.622083887
#Sta/Elev= 30
       0 2134.07    22.6 2125.01    45.5 2114.22    77.9 2097.19   114.1 2082.31
   140.1 2068.97   167.4 2056.89   194.1 2048.49   228.4 2041.07   251.3 2031.76
   308.5 2026.77   341.3 2025.97   369.5 2023.81   388.5 2024.54  399.722022.037
   407.6 2020.19     419 2020.59  425.952022.194   434.7 2024.29   444.3 2024.87
   468.6 2023.52   521.9 2023.38   533.4 2024.97     541  2028.6   578.4 2053.36
   590.5 2058.24     602    2064   628.6 2068.05   655.3 2077.19   750.3  2100.6
#Mann= 5 ,-1 , 0
       0      .1       0  358.78     .06       0  399.72    .045       0
  425.95     .06       0  455.51      .1       0
#XS Ineff= 2 , 0
          382.75 2026.15
Permanent Ineff=
       F       F
Bank Sta=399.72,425.95
XS Rating Curve= 0 ,0
Exp/Cntr=0.3,0.1

Type RM Length L Ch R = 1 ,3952    ,314.7,313.6,311.8
XS GIS Cut Line= 2
2145569.91776064373865.5525283072144925.82029556373431.524853066
#Sta/Elev= 30
       0  2160.2    63.9 2151.88    83.6 2148.05   110.1 2140.98   154.9 2126.09
   195.2 2110.42   225.6 2096.33   277.5 2077.77     302 2067.73   325.2 2057.58
   340.8 2049.05   348.7 2043.47   358.3 2034.13   379.5 2032.39   396.7 2021.49
     408 2017.51   427.8  2015.1   467.4 2016.59   483.2 2015.26   510.9 2016.38
  517.48 2014.77   526.7 2013.25  537.532015.318   554.4 2017.31   578.1 2017.71
   609.8  2023.9   651.3 2044.22   693.9 2056.27   712.7 2062.78   776.7 2088.68
#Mann= 5 ,-1 , 0
       0      .1       0  371.77     .06       0  412.58      .1       0
  517.48    .045       0  537.53      .1       0
Bank Sta=517.48,537.53
XS Rating Curve= 0 ,0
Exp/Cntr=0.3,0.1

Type RM Length L Ch R = 1 ,3639    ,291.9,292.8,292.9
XS GIS Cut Line= 2
2145722.69534223373619.0248061422145097.69527988373207.566311479
#Sta/Elev= 30
       0 2209.94    47.4 2190.31    92.4 2168.21     154 2141.07   183.5 2126.87
   196.6 2119.04   213.2 2114.59   260.5 2091.31   305.6  2072.8     334 2059.77
   356.3 2045.05   374.2 2044.06     379 2042.66   387.7 2036.85   402.7 2029.32
   416.9 2020.76  434.592006.826   454.5 2004.93     4642007.255   474.1 2009.31
   525.2 2007.14   544.8 2007.81   575.6 2012.22   592.2  2021.4   622.9  2036.6
   672.7 2055.47     702 2068.98   709.8 2071.09   721.6  2077.8   748.3  2090.6
#Mann= 5 ,-1 , 0
       0      .1       0  339.58     .06       0  434.59    .045       0
     464     .06       0   491.6      .1       0
Bank Sta=434.59,464
XS Rating Curve= 0 ,0
Exp/Cntr=0.3,0.1