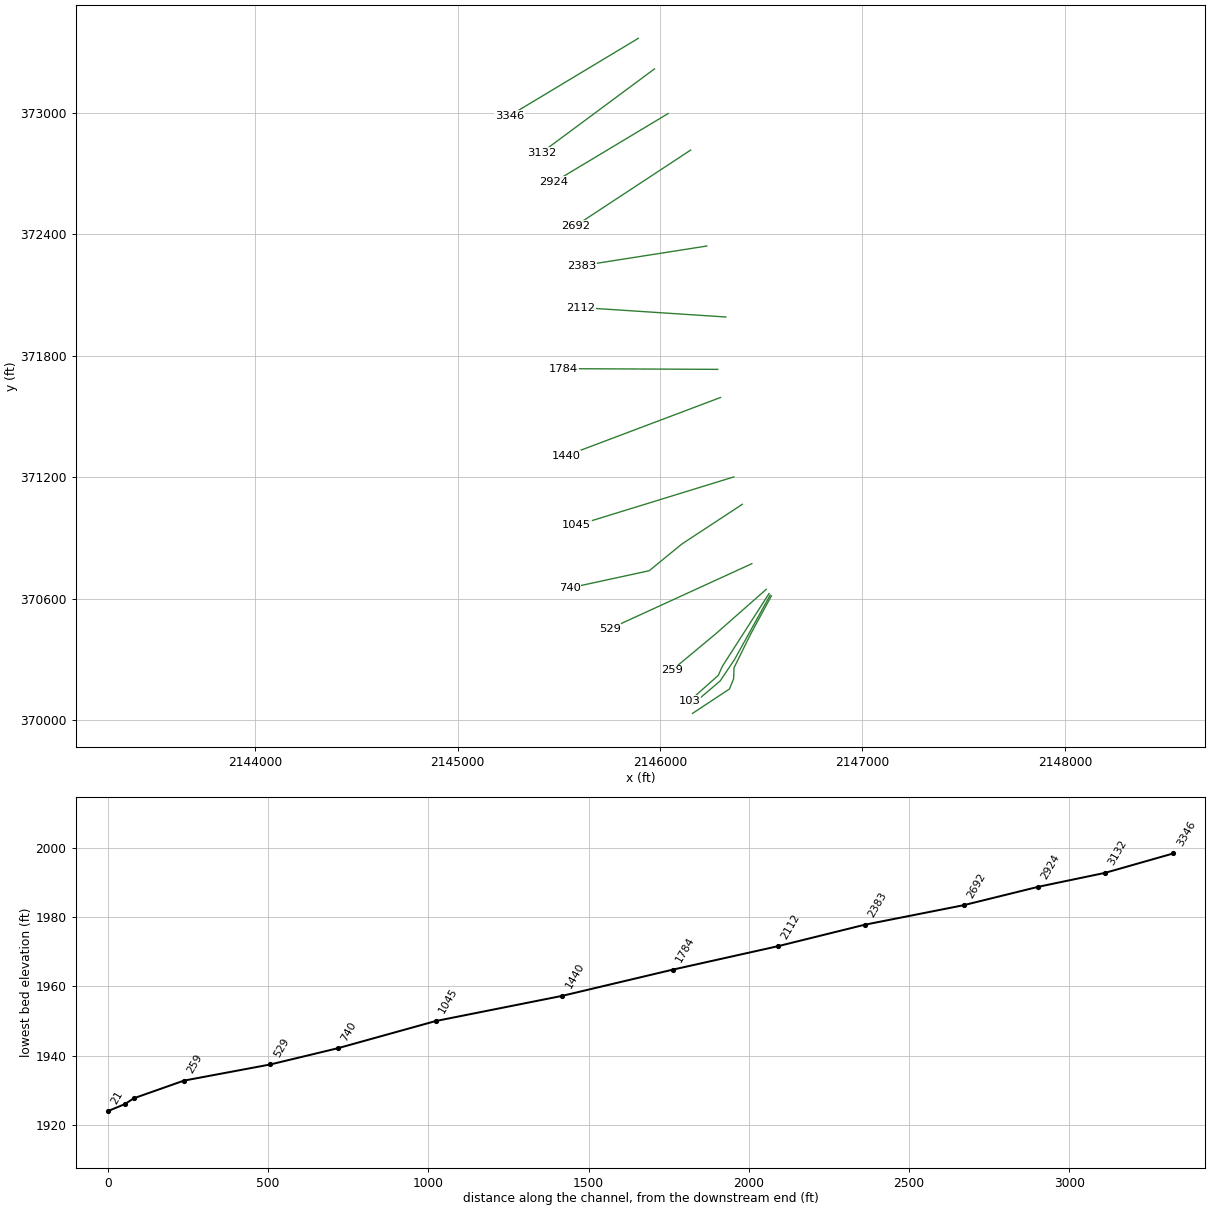
HEC-RAS study DRYRN.prj: DRYRN

--- DRYRN.g01 (geometry) --- (continued)

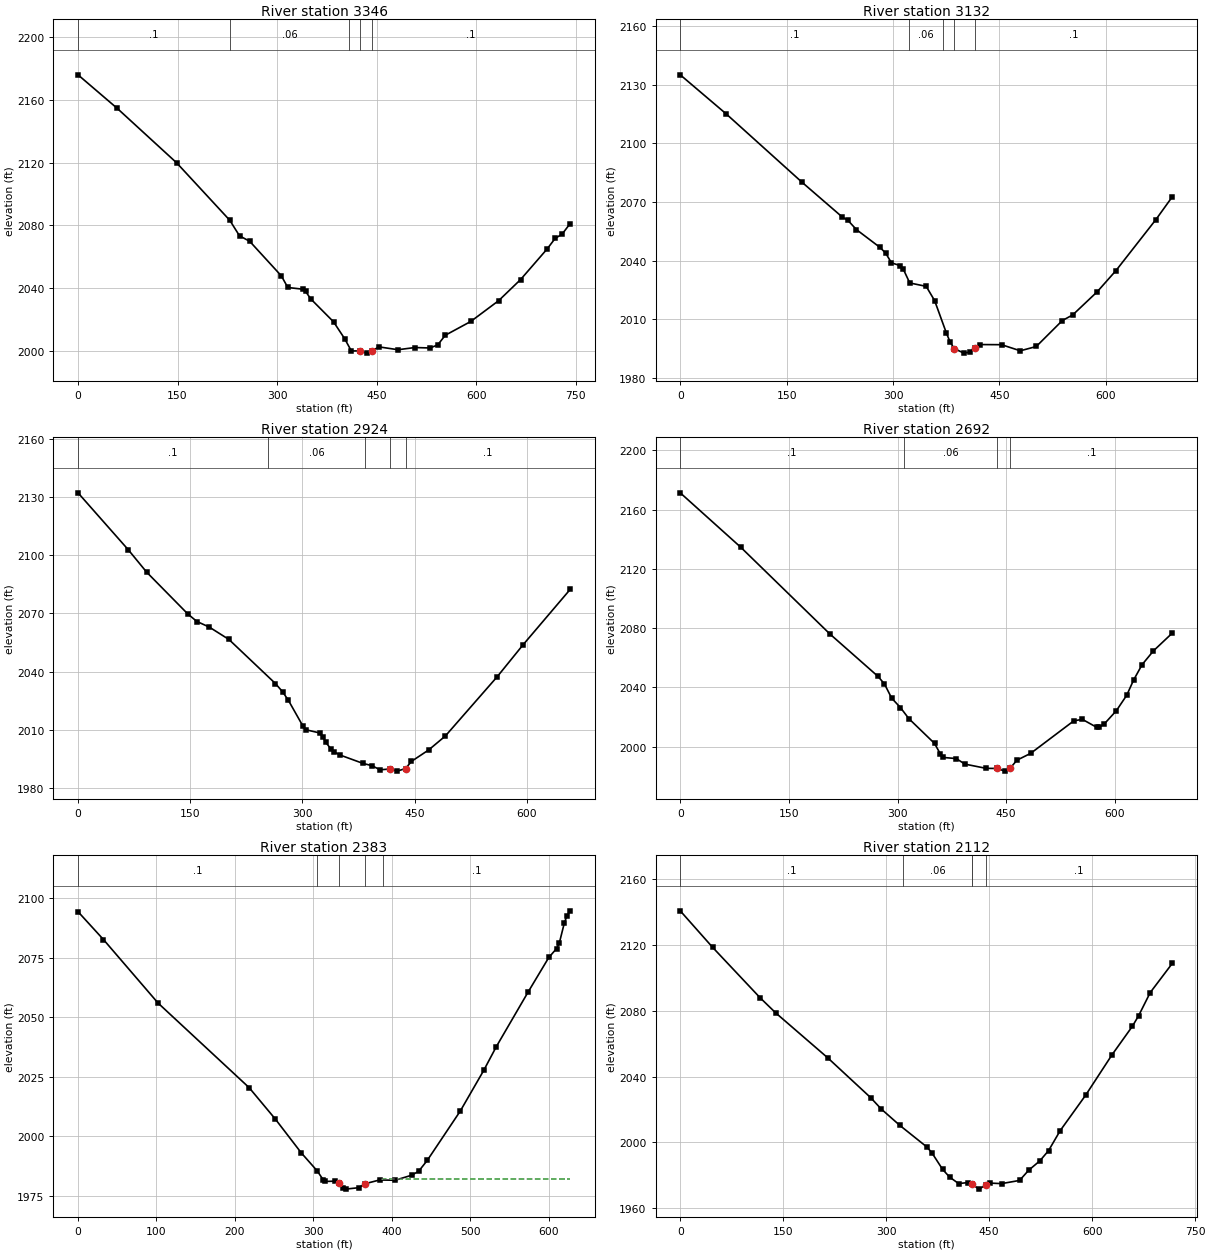
Type RM Length L Ch R = 1 ,3346    ,212.3,213.5,213.3
XS GIS Cut Line= 2
2145892.83443764373369.0246499782145257.41772947372987.080203891
#Sta/Elev= 30
       0 2176.01      59 2154.63   148.5 2119.87   228.7 2083.13   243.3 2073.23
   258.6 2069.76   306.3 2047.69   316.1 2040.25   338.7 2039.16   342.9 2037.73
   350.8  2032.9     385 2018.33   401.8 2007.51   411.8 1999.74  425.071999.778
   434.7 1998.35  442.861999.964   453.9 2002.31   482.1 2000.52   507.5 2001.92
   530.4 2001.64   541.9 2003.59   553.4 2009.77   591.7 2018.55   633.8 2031.86
   666.7 2045.27   706.9  2064.9   718.8 2071.55   729.5 2074.37   741.4 2081.02
#Mann= 5 ,-1 , 0
       0      .1       0  228.98     .06       0  408.64      .1       0
  425.07    .045       0  442.86      .1       0
Bank Sta=425.07,442.86
XS Rating Curve= 0 ,0
Exp/Cntr=0.3,0.1

Type RM Length L Ch R = 1 ,3132    ,210.4,208.1,203.3
XS GIS Cut Line= 2
2145972.69549839373217.9829573042145415.40363397372804.788573727
#Sta/Elev= 30
       0 2134.95      65 2114.92   171.4 2080.15   228.3 2062.33   236.5 2060.54
   248.5 2055.84   281.4 2046.82   289.6 2043.87   297.8 2038.87     310 2037.47
   314.2 2035.87   323.6 2028.59   346.8 2026.85   358.7 2019.55   375.4 2002.86
   380.4 1998.51  386.151995.087   399.9 1992.73     408 1993.24   415.6 1995.31
   422.1 1997.11     453 1997.04   479.5 1993.92     502 1996.12   538.7 2009.37
   553.4 2012.26   587.8 2024.05   614.4 2034.93   670.7    2061   693.8 2072.64
#Mann= 5 ,-1 , 0
       0      .1       0  322.87     .06       0  370.09      .1       0
  386.15    .045       0   415.6      .1       0
Bank Sta=386.15,415.6
XS Rating Curve= 0 ,0
Exp/Cntr=0.3,0.1

Type RM Length L Ch R = 1 ,2924    ,232.1,232.8,232.7
XS GIS Cut Line= 2
 2146040.4036963372997.4968497312145476.16762005 372658.95520398
#Sta/Elev= 30
       0 2132.19    67.1 2102.88    91.8 2091.28   146.8 2069.74     159 2065.85
   175.5 2062.98   201.8 2056.59     264 2033.85   273.6  2029.6   281.4 2025.14
   300.5  2012.1   304.3 2010.07   323.5 2008.37   327.3 2006.48   331.1 2003.66
   338.1 2000.18   342.9 1998.55   350.1 1997.05   381.2 1992.67   393.1 1991.53
   403.8 1989.38   417.61989.832   426.8 1988.71  437.931990.048   445.9 1993.75
   468.9 1999.63   491.2 2006.82   560.7 2037.46   595.1 2053.84     658 2082.35
#Mann= 5 ,-1 , 0
       0      .1       0  253.66     .06       0   383.8      .1       0
   417.6    .045       0  437.93      .1       0
Bank Sta=417.6,437.93
XS Rating Curve= 0 ,0
Exp/Cntr=0.3,0.1

Type RM Length L Ch R = 1 ,2692    ,313,308.9,301.8
XS GIS Cut Line= 2
2146151.51502264372816.9414365592145583.80651239372443.677419305
#Sta/Elev= 30
       0 2171.37    83.5 2134.64   206.6 2076.04     273 2047.41     282 2042.26
   291.9  2032.7     304 2026.34   315.7 2018.83   351.1 2002.12   358.9 1995.23
   362.9 1992.65   381.1 1991.88     393 1988.14   422.2 1985.29  437.371985.194
   448.3  1983.4  455.661985.464   464.9  1990.8   483.8 1995.39   543.5  2017.4
   555.3 2018.34   574.9 2013.02   578.8 2013.15   585.7  2015.4   602.1 2024.19
   616.5 2034.68   625.9 2044.88   637.7 2055.34   653.4 2064.66   679.4 2076.65
#Mann= 4 ,-1 , 0
       0      .1       0  309.23     .06       0  437.37    .045       0
  455.66      .1       0
Bank Sta=437.37,455.66
XS Rating Curve= 0 ,0
Exp/Cntr=0.3,0.1

Type RM Length L Ch R = 1 ,2383    ,272.5,270.4,266.1
XS GIS Cut Line= 2
2146231.37608339372342.9830668872145611.58434397372245.760820389
#Sta/Elev= 30
       0 2094.35    32.4 2082.65   102.1 2055.93   218.2 2020.39   251.6 2007.18
   284.8 1992.93   304.9 1985.44   312.7 1981.63   314.7 1980.98     328  1981.1
  332.451980.252   337.9 1978.17   341.2 1977.75   357.8 1978.35  365.971980.017
   384.4 1981.59   404.3 1981.48   425.2 1983.58   434.2 1985.22   445.3 1989.83
   487.4 2010.57   517.3 2027.66   533.3 2037.61   573.7 2060.49   600.3 2075.13
   610.2 2078.86   613.6 2081.09   620.2  2089.8   623.5 2092.66   627.4 2094.71
#Mann= 5 ,-1 , 0
       0      .1       0  304.37     .06       0  332.45    .045       0
  365.97     .06       0  389.28      .1       0
#XS Ineff= 1 ,-1
   387.4  627.37 1981.83
Permanent Ineff=
       F
Bank Sta=332.45,365.97
XS Rating Curve= 0 ,0
Exp/Cntr=0.3,0.1

Type RM Length L Ch R = 1 ,2112    ,322.4,328.1,327.1
XS GIS Cut Line= 2
2146325.12589589371992.2885583042145609.84812698372039.163464561
#Sta/Elev= 30
       0 2140.93    47.1 2118.74   116.8 2087.83   139.2 2078.77   214.8 2051.49
   277.3 2027.28   292.7 2020.36     320 2010.31   359.5 1997.13   366.8 1993.53
   382.2 1983.57   392.3 1978.93   405.5 1974.94   418.6 1975.53   425.11974.545
   435.1 1971.56  445.221974.083   451.5 1975.23     468 1974.91   494.3 1976.85
   507.4 1982.98   523.9 1988.79   536.5 1994.97   553.4 2007.11   590.4 2028.63
     629 2053.33   658.7  2070.7   667.8 2077.16   684.6 2091.17   716.8 2108.96
#Mann= 5 ,-1 , 0
       0      .1       0  324.72     .06       0   424.5      .1       0
   425.1    .045       0  445.22      .1       0
Bank Sta=425.1,445.22
XS Rating Curve= 0 ,0
Exp/Cntr=0.3,0.1

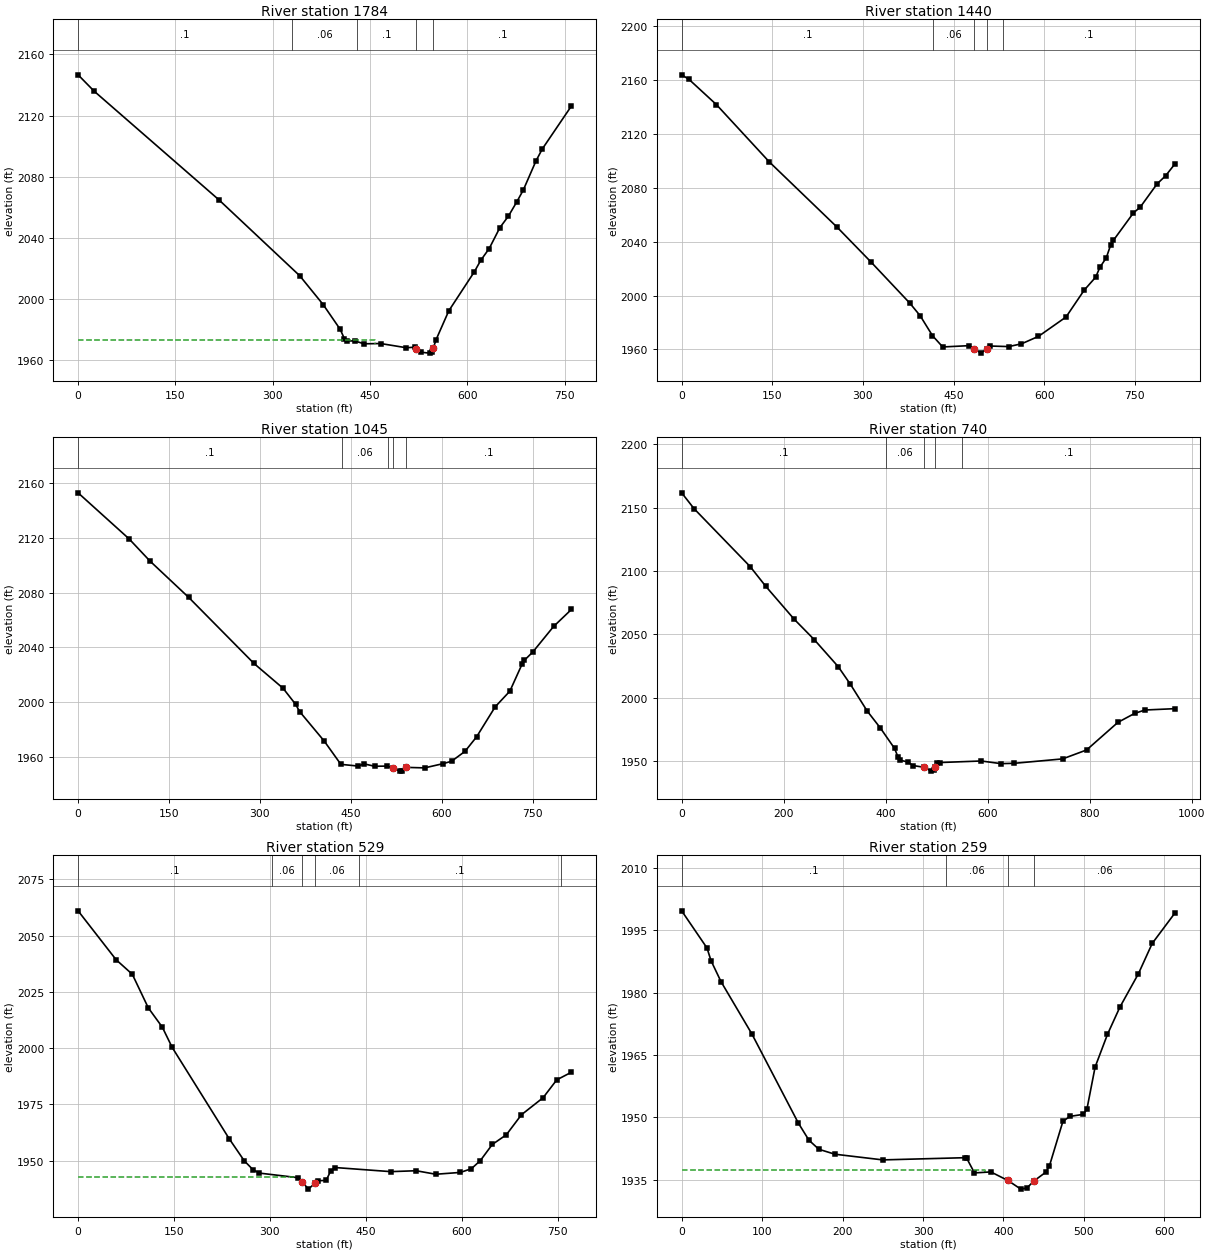
Type RM Length L Ch R = 1 ,1784    ,337.1,344.6,346.7
XS GIS Cut Line= 2
2146285.19552955371733.607973307 2145524.7787433371737.080407307
#Sta/Elev= 30
       0 2146.67    24.6 2136.05   217.1 2064.97   341.7 2015.34   377.8  1996.5
   404.1 1980.29   410.6 1974.12   413.9 1972.84     427 1972.69   440.9 1970.88
   466.4 1971.06   505.8 1968.32   518.9 1968.66  521.15 1967.74   528.7 1965.36
   541.9 1964.79   545.1 1965.55  547.371967.907   551.7 1973.46   571.4 1992.43
   610.8 2017.95   620.6 2025.39   633.7 2033.14   650.1 2046.77   663.3 2054.31
   676.4 2063.78   686.2 2071.33   705.9 2090.49   715.7 2098.33   760.4 2126.28
#Mann= 5 ,-1 , 0
       0      .1       0  329.27     .06       0  429.82      .1       0
  521.15    .045       0  547.37      .1       0
#XS Ineff= 2 , 0
          457.86 1973.07
Permanent Ineff=
       F       F
Bank Sta=521.15,547.37
XS Rating Curve= 0 ,0
Exp/Cntr=0.3,0.1

Type RM Length L Ch R = 1 ,1440    ,395.2,394.9,394
XS GIS Cut Line= 2
2146299.08428131 371594.719143482145535.19538914371306.524837971
#Sta/Elev= 30
       0 2163.93    11.9 2160.65    57.5 2141.81   145.1 2099.23   257.4  2050.7
   313.5 2024.83   377.9 1994.19   394.8 1984.94   415.1  1970.2     432 1961.81
   474.8 1962.76  484.481960.224   495.6 1957.23  504.721960.592   509.8 1962.52
   541.2 1962.09   562.4 1964.14   590.5 1969.68   636.1 1984.06   666.2 2004.03
   685.2 2013.67   692.2 2021.03   702.7 2027.99   709.7 2037.24   714.6 2041.06
   747.7  2061.4   758.8 2065.59   786.8 2082.94   800.9 2088.95   816.4  2097.8
#Mann= 5 ,-1 , 0
       0      .1       0  416.61     .06       0  484.48    .045       0
  504.72     .06       0  531.17      .1       0
Bank Sta=484.48,504.72
XS Rating Curve= 0 ,0
Exp/Cntr=0.3,0.1

Type RM Length L Ch R = 1 ,1045    ,299.3,304.6,307.8
XS GIS Cut Line= 2
 2146365.0565903371202.3580515532145587.27861831370962.774869308
#Sta/Elev= 30
       0 2152.65    84.1 2119.13   118.6 2102.96   182.6 2076.42   290.1  2028.4
   338.1 2010.32   358.7  1998.7   365.6 1993.26   405.9 1971.93   433.5 1954.89
   461.7 1953.65     472 1955.21   489.2 1953.49   509.7 1953.62  519.721952.095
   530.4 1949.95   533.8    1950  540.181952.698   571.6 1952.31   602.5 1955.43
   616.2 1957.16   638.3 1964.36   657.4 1974.93   688.1 1996.79   712.3 2008.21
   732.9 2028.34   736.4 2030.75   750.1  2036.7   784.4  2055.3   813.8 2067.68
#Mann= 5 ,-1 , 0
       0      .1       0  434.99     .06       0  511.29      .1       0
  519.72    .045       0  540.18      .1       0
#XS Ineff= 2 , 0
          470.93 1954.84
Permanent Ineff=
       F       F
Bank Sta=519.72,540.18
XS Rating Curve= 0 ,0
Exp/Cntr=0.3,0.1

Type RM Length L Ch R = 1 ,740     ,214.1,211.5,208.9
XS GIS Cut Line= 4
2146406.72317363371066.941327646 2146108.1122223370870.760945722
 2145946.6538838370738.8163277212145554.29279189370653.746944055
#Sta/Elev= 30
       0 2161.68    24.3 2149.19   134.3  2103.5   164.9 2087.93   220.6 2061.98
   259.9 2045.89     307 2024.53   330.8 2010.66   363.8 1989.53   389.5 1976.21
   417.5 1959.99   424.4 1953.08   427.9 1950.78   443.1 1949.39   453.8 1946.53
  474.581945.192   489.7 1942.12   494.4 1943.03  497.381945.363   501.4 1948.42
   505.7 1948.89   587.5 1950.12   626.1 1948.03   652.4  1948.3     747 1951.77
     794 1958.82   855.4 1980.59     888 1987.62   908.1 1990.33   967.3  1991.4
#Mann= 5 ,-1 , 0
       0      .1       0  401.15     .06       0  474.58    .045       0
  497.38     .06       0  550.27      .1       0
Bank Sta=474.58,497.38
XS Rating Curve= 0 ,0
Exp/Cntr=0.3,0.1

Type RM Length L Ch R = 1 ,529     ,263.9,269.2,274.4
XS GIS Cut Line= 2
2146453.59807989370773.538699225 2145752.2093908 370452.35791114
#Sta/Elev= 30
       0 2061.02    59.5 2039.29    84.8 2032.84   109.8 2017.92   131.7 2009.35
   147.2 2000.32   236.3 1959.78   259.9 1949.98   273.4 1946.07   283.3 1944.54
   344.6 1942.47  350.42 1940.69   360.1 1937.41  370.421940.021   374.9 1941.15
   387.9 1941.27   395.1 1945.53   402.1    1947   488.9 1945.18   528.6 1945.58
   559.4 1944.02   597.7 1944.83     615 1946.47   629.1 1950.11   647.7 1957.25
   669.7 1961.56   693.3 1970.45   727.1    1978   748.5 1985.94   771.4 1989.33
#Mann= 6 ,-1 , 0
       0      .1       0  303.06     .06       0  350.42    .045       0
  370.42     .06       0  438.86      .1       0  754.94     .06       0
#XS Ineff= 2 , 0
          340.12 1942.71
Permanent Ineff=
       F       F
Bank Sta=350.42,370.42
XS Rating Curve= 0 ,0
Exp/Cntr=0.3,0.1

Type RM Length L Ch R = 1 ,259     ,152.2,156.1,160.3
XS GIS Cut Line= 3
2146524.77871181 370646.802404152146276.51477264370428.052513555
2146059.50109905370247.497100398
#Sta/Elev= 30
       0 1999.69    31.5 1990.75    36.5  1987.7    48.9 1982.66    87.3 1970.07
   145.1 1948.62   158.2 1944.52   170.5 1942.34   190.4 1941.15     250 1939.78
     352 1940.31   354.4 1940.15     364 1936.65   384.3 1936.89  405.52 1934.83
   421.6 1932.75   429.2 1933.03  437.971934.728   452.4 1936.79   457.1 1938.31
   473.9 1949.05   482.5 1950.24   499.1 1950.73   503.7 1951.94   513.9  1962.1
   529.3 1969.98   544.7 1976.52   567.8 1984.58   584.9 1991.85   613.2 1999.18
#Mann= 4 ,-1 , 0
       0      .1       0  329.03     .06       0  405.52    .045       0
  437.97     .06       0
#XS Ineff= 2 , 0
          377.47 1937.24
Permanent Ineff=
       F       F
Bank Sta=405.52,437.97
XS Rating Curve= 0 ,0
Exp/Cntr=0.5,0.3

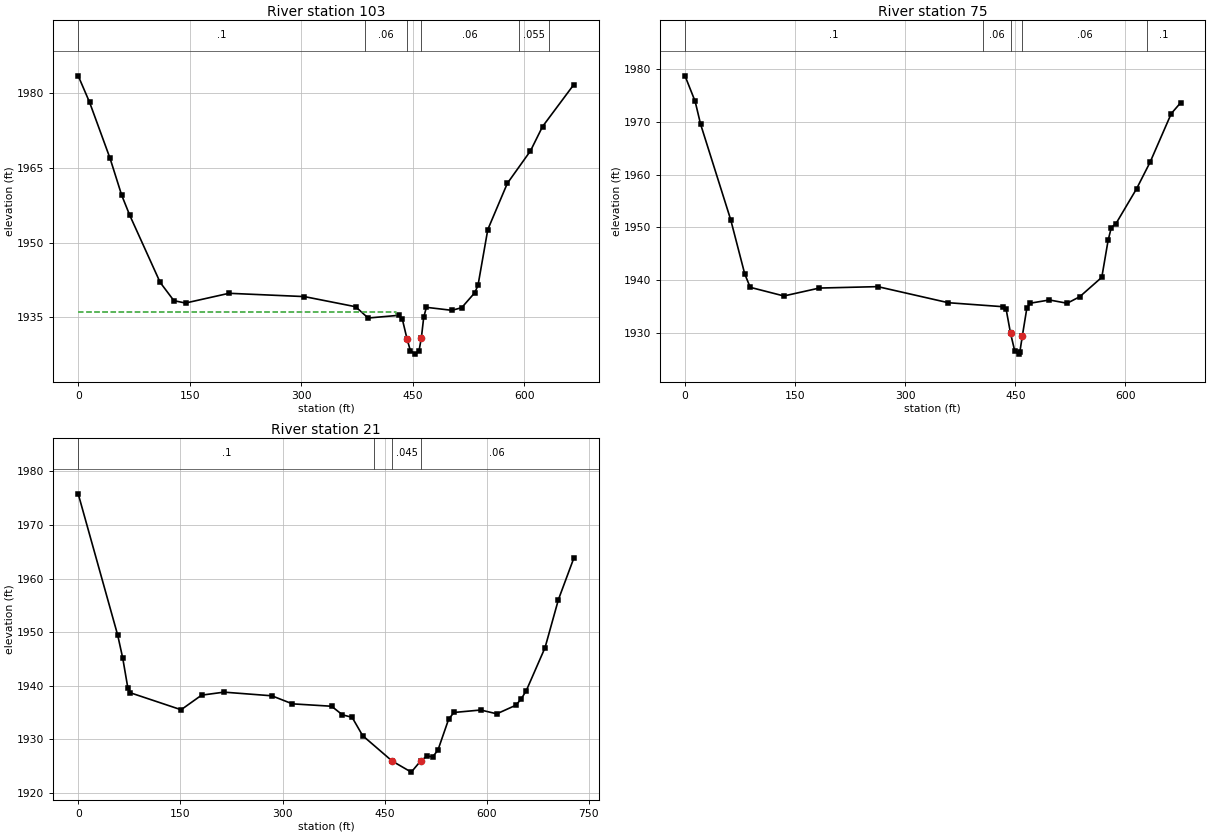
Type RM Length L Ch R = 1 ,103     ,29.1,28,25.5
XS GIS Cut Line= 4
2146538.66779163370625.9691124712146308.18137597370266.918321401
2146288.04263672370221.7793040572146145.68137288370095.390449226
#Sta/Elev= 30
       0 1983.38    15.3 1978.08    42.9 1966.83    58.5 1959.47    69.3 1955.47
   110.2 1942.02   128.7 1938.36   144.3 1937.89   202.8 1939.84   304.1 1939.18
     373 1937.15   389.9 1934.89     431 1935.43   435.9 1934.64  442.111930.769
   446.7 1928.35   453.3 1927.66   458.3  1928.3  461.511930.976   464.6    1935
   468.2 1937.03   502.5 1936.43   515.7 1936.96   533.2 1939.94   537.6 1941.41
   550.8  1952.6   577.1 1961.86   608.2 1968.35   624.4 1973.22   666.5 1981.63
#Mann= 6 ,-1 , 0
       0      .1       0  385.83     .06       0  442.11    .045       0
  461.51     .06       0   592.5    .055       0  632.78      .1       0
#XS Ineff= 2 , 0
          427.43 1936.08
Permanent Ineff=
       F       F
Bank Sta=442.11,461.51
XS Rating Curve= 0 ,0
Exp/Cntr=0.5,0.3

Type RM Length L Ch R = 1 ,75      ,51.8,53.9,69.1
XS GIS Cut Line= 4
2146544.29278038370618.3070543112146367.90369748 370299.55703564
 2146297.0705058370194.0014724732146156.79257114370075.251709983
#Sta/Elev= 30
       0 1978.76    13.8 1973.92    21.2 1969.61    62.3 1951.45    81.3 1941.23
    88.8 1938.65   134.7 1937.01     183 1938.51   262.6 1938.78   358.7 1935.73
   433.5 1934.97   437.5 1934.48  443.461929.942   449.1 1926.64   454.8 1925.98
   456.2 1926.41  459.491929.369   465.7  1934.7   470.4 1935.64   496.4 1936.25
   520.6 1935.63   537.7 1936.86   567.8 1940.55   576.4 1947.55   580.7 1949.96
   587.1 1950.73   615.1 1957.32   633.7 1962.41   662.4 1971.59   675.2 1973.66
#Mann= 5 ,-1 , 0
       0      .1       0  405.52     .06       0  443.46    .045       0
  459.49     .06       0  629.75      .1       0
Bank Sta=443.46,459.49
XS Rating Curve= 0 ,0
Exp/Cntr=0.5,0.3

Type RM Length L Ch R = 1 ,21      ,15.84,18,10.03
XS GIS Cut Line= 6
2146550.31835888370614.5659200552146447.23687214370424.678504556
2146365.85645747370259.748060137 2146363.6865143370204.409588143
2146343.07008572370154.4963021432146160.77845556370034.053629637
#Sta/Elev= 30
       0 1975.79      58 1949.44    65.4 1945.16    72.9 1939.61    76.6  1938.7
   151.1 1935.54   181.2 1938.26   214.1 1938.82   284.3 1938.14   314.5 1936.64
   372.1 1936.19     388 1934.59   402.2 1934.13   417.7 1930.71  461.041925.973
   489.1 1923.91  503.011926.018   512.5 1926.93   520.4 1926.74   528.2    1928
     544 1933.79   551.8 1935.03   591.1 1935.49   614.7 1934.78   642.3 1936.36
   650.1 1937.46     658 1939.11   685.5 1947.11   705.2 1956.09   727.8 1963.81
#Mann= 4 ,-1 , 0
       0      .1       0  435.03     .06       0  461.04    .045       0
  503.01     .06       0
Bank Sta=461.04,503.01
XS Rating Curve= 0 ,0
Exp/Cntr=0.3,0.1
LCMann Table=0

Chan Stop Cuts=-1
Use User Specified Reach Order=0
Composite Channel Slope=5